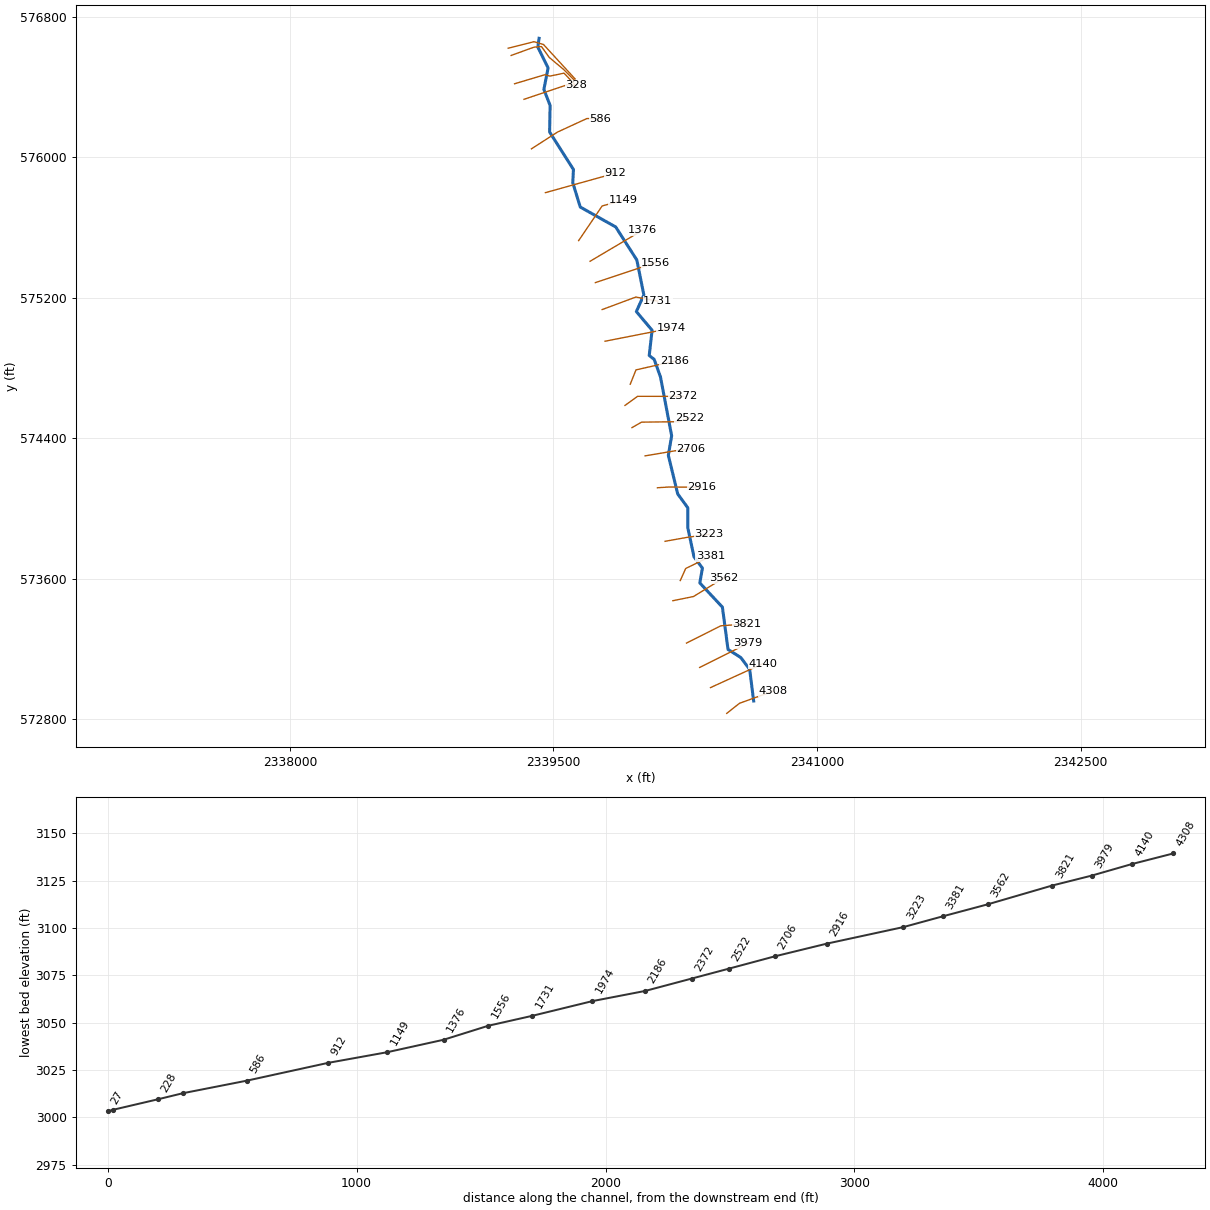
--- LONGRN.prj (project) ---

Proj Title=LONGRN
Current Plan=p01
Default Exp/Contr=0,0
English Units
Geom File=g01
Flow File=f01
Plan File=p01
BEGIN DESCRIPTION:
----------MODEL BY WOOD PLC 2021----------
Stream Name: Long Run
Flood Zone: Enhanced Approximate
Pocahontas County, WV
HEC-RAS Version: RAS 6.1
Vertical Datum: NAVD88
Projection: NAD 1983 StatePlane West Virginia S FIPS 4702 (US Feet)
Terrain: 1-meter LIDAR (FEMA Region III 3DEP collected 2016-2018)
Land Use: 2019 NLCD
Hydrologic Method:
WV SIR2010-5033 regression equations
Model Notes:
END DESCRIPTION:
DSS File=dss
DSS Export Rating Curves= 0
DSS Export Rating Curve Sorted= 0
DSS Export Volume Flow Curves= 0
DXF OffsetX= 0
DXF OffsetY= 0
DXF ScaleX= 0
DXF ScaleY= 0

--- LONGRN.p01 (plan) ---

Plan Title=Floodplain
Program Version=6.10
Short Identifier=Floodplain
Geom File=g01
Flow File=f01
Subcritical Flow
K Sum by GR= 0
Std Step Tol= 0.01
Critical Tol= 0.01
Num of Std Step Trials= 20
Max Error Tol= 0.3
Flow Tol Ratio= 0.001
Split Flow NTrial= 30
Split Flow Tol= 0.02
Split Flow Ratio= 0.02
Log Output Level= 0
Friction Slope Method= 1
Unsteady Friction Slope Method= 2
Unsteady Bridges Friction Slope Method= 1
Parabolic Critical Depth
Global Vel Dist= 0 , 0 , 0
Global Log Level= 0
CheckData=True
Encroach Param=-1 ,0,0, 0
Computation Interval=0.1SEC
Output Interval=1SEC
Instantaneous Interval=Max Profile
Mapping Interval=1HOUR
Computation Time Step Use Courant=        0
Computation Time Step Use Time Series=    0
Computation Time Step Count To Double=0
Computation Time Step Max Doubling=0
Computation Time Step Max Halving=0
Computation Time Step Residence Courant=0
Run HTab= 0
Run UNet= 0
Run Sediment= 0
Run PostProcess= 0
Run WQNet= 0
Run RASMapper=-1
UNET Theta= 0
UNET Theta Warmup= 0
UNET ZTol= 0
UNET ZSATol= 0
UNET MxIter= 0
UNET Max Iter WO Improvement= 0
UNET MaxInSteps= 0
UNET DtIC= 0
UNET DtMin= 0
UNET MaxCRTS= 0
UNET WFStab= 0
UNET SFStab= 0
UNET WFX= 1
UNET SFX= 1
UNET Gravity=32.174
UNET 1D Methodology=Finite Difference
UNET DSS MLevel= 1
UNET Pardiso=0
UNET DZMax Abort= 0
UNET Use Existing IB Tables= 0
UNET Froude Reduction=False
UNET Froude Limit= 0
UNET Froude Power= 0
UNET D1 Cores= 0
UNET WindReference=Eulerian
UNET WindDragFormulation=Hsu (1988)
UNET D2 Coriolis=0
UNET D2 Cores= 0
UNET D2 Theta= 1
UNET D2 Theta Warmup= 1
UNET D2 Z Tol= 0.01
UNET D2 Volume Tol= 0.01
UNET D2 Max Iterations= 20
UNET D2 Equation= 0
UNET D2 RampUpFraction=0.1
UNET D2 TimeSlices= 1
UNET D2 Turbulence Formulation=Non-Conservative (original)
UNET D2 Eddy Viscosity=0.3
UNET D2 Transverse Eddy Viscosity=0.1
UNET D2 Smagorinsky Mixing=0
UNET D2 BCVolumeCheck=0
UNET D2 Cores=0
UNET D2 SolverType=PARDISO (Direct)
UNET D2 Minimum Iterations= 2147483647
UNET D2 Maximum Iterations= 2147483647
UNET D2 Restart Number= 10
UNET D2 Relaxation Coeff=1.3
UNET D2 SOR Precondition Iterations= 10
UNET D2 ILUT Maximum Fill= 8
UNET D2 ILUT Tolerance=1E-08
UNET D1D2 MaxIter= 0
UNET D1D2 ZTol=0.01
UNET D1D2 QTol=0.1
UNET D1D2 MinQTol=1
Write IC File= 0
Write IC File at Fixed DateTime=0
Write IC File at Sim End=0
Echo Input=False
Echo Parameters=False
Echo Output=False
Write Detailed= 0
HDF Write Warmup=0
HDF Write Time Slices=0
HDF Flush=0
HDF Compression= 1
HDF Chunk Size= 1
HDF Spatial Parts= 1
HDF Use Max Rows=0
HDF Fixed Rows= 1
Calibration Method= 0
Calibration Iterations= 20
Calibration Max Change=0.05
Calibration Tolerance=0.2
Calibration Maximum=1.5
Calibration Minimum=0.5
Calibration Optimization Method= 1
WQ AD Non Conservative
WQ ULTIMATE=-1
WQ Max Comp Step=1HOUR
WQ Output Interval=15MIN
WQ Output Selected Increments= 0
WQ Output face flow=0
WQ Output face velocity=0
WQ Output face area=0
WQ Output face dispersion=0
WQ Output cell volume=0
WQ Output cell surface area=0
WQ Output cell continuity=0
WQ Output cumulative cell continuity=0
WQ Output face conc=0
WQ Output face dconc_dx=0
WQ Output face courant=0
WQ Output face peclet=0
WQ Output face adv mass=0
WQ Output face disp mass=0
WQ Output cell mass=0
WQ Output cell source sink temp=0
WQ Output nsm pathways=0
WQ Output nsm derived pathways=0
WQ Create Restart=0
WQ Fixed Restart=0
WQ System Summary=0
WQ Write To DSS=0
Sorting and Armoring Iterations= 10
XS Update Threshold= 0.02
Bed Roughness Predictor= 0
Hydraulics Update Threshold= 0.02
Energy Slope Method= 1
Volume Change Method= 1
Sediment Retention Method= 0
Sediment TS Multiplier= 1
Warm Up Method= 0
XS Weighting Method= 0
Number of US Weighted Cross Sections= 1
Number of DS Weighted Cross Sections= 1
Upstream XS Weight=0
Main XS Weight=1
Downstream XS Weight=0
Number of DS XS's Weighted with US Boundary= 1
Upstream Boundary Weight= 1
Weight of XSs Associated with US Boundary= 0
Number of US XS's Weighted with DS Boundary= 1
Downstream Boundary Weight= 0.5
Weight of XSs Associated with DS Boundary= 0.5
Percentile Method= 0
Sediment Output Level= 3
Mass or Volume Output= 0
Output Increment Type= 1
Profile and TS Output Increment= 1
Transport Output Increment 1
XS Output Flag= 0
XS Output Increment= 10
Read HDF5 Sediment Hotstart= 0
Sediment Hotstart Type= 0
Write Gradation File= 0
Read Gradation Hotstart= 0
Write HDF5 File= 1
Write Binary Output= 1
Write DSS Sediment File= 0
DSS Sediment Output Type= 1
SV Curve= 0
Specific Gage Flag= 0
Subcell Erosion Methods= 0
Subcell Deposition Methods= 0
Advection Scheme= 1
Matrix Solver= 0
Implicit Weighting Factor= 1
Maximum Outer Loop Convergence Iterations= 5
Convergence Maximum Absolute= 0.001
Convergence RMSE= 0.0001
Grain Fractions Max Abs Error= 0.001
Max Subgrid Regions= 1
Max Subgrid Length Scale= 3.402823E+38
Initial Layer Thickness= 3.402823E+38
Min Layer Thickness= 3.402823E+38
Max Layer Thickness= 3.402823E+38
Number of Layers= 5

--- LONGRN.f01 (steady flow) ---

Flow Title=Flow
Program Version=6.10
Number of Profiles= 6
Profile Names=01pct,10pct,04pct,02pct,0_2pct,01plus
River Rch & RM=LONGRN,Main            ,4308
     526     277     369     445     736     778
River Rch & RM=LONGRN,Main            ,328
     586     310     412     496     818     867
Boundary for River Rch & Prof#=LONGRN,Main            , 1
Up Type= 0
Dn Type= 3
Dn Slope=0.03477
Boundary for River Rch & Prof#=LONGRN,Main            , 2
Up Type= 0
Dn Type= 3
Dn Slope=0.03477
Boundary for River Rch & Prof#=LONGRN,Main            , 3
Up Type= 0
Dn Type= 3
Dn Slope=0.03477
Boundary for River Rch & Prof#=LONGRN,Main            , 4
Up Type= 0
Dn Type= 3
Dn Slope=0.03477
Boundary for River Rch & Prof#=LONGRN,Main            , 5
Up Type= 0
Dn Type= 3
Dn Slope=0.03477
Boundary for River Rch & Prof#=LONGRN,Main            , 6
Up Type= 0
Dn Type= 3
Dn Slope=0.03477
DSS Import GetInterval= 0
DSS Import GetPeak= 0
DSS Import FillOption= 0

--- LONGRN.g01 (geometry) ---

Geom Title=Geometry
Program Version=6.10

River Reach=LONGRN          ,Main
Reach XY= 30
2340639.25334297572905.0757083152340616.73993656573084.304024398
2340565.86700681573152.414780557 2340493.3415613573198.452746227
2340461.38821314573439.1533803052340332.84450696573576.789916053
2340347.65976605573661.3547075542340299.72974381573725.471377224
2340264.41321339573891.1236049832340264.62318672574004.221475899
 2340207.0232363574083.473942056 2340153.6276738574303.152636558
2340172.54758348 574414.358450892340108.85118856 574749.86762239
2340073.11405531574849.090849146 2340044.9448203574871.163967729
2340061.13146771575015.1636797342339971.57816914575121.324228555
2340014.25262447575216.133094057 2339974.3111033575414.999822304
2339854.27295755575602.7510872332339652.25597313575716.453615725
2339609.82889263575854.985162809 2339613.5756043575930.036193803
2339477.92626931576143.2995468082339480.71727422576294.555477887
2339445.37187247576385.6944032312339469.33770381 576508.21712406
2339410.80599672576626.5928715622339417.79909296 576676.49270615

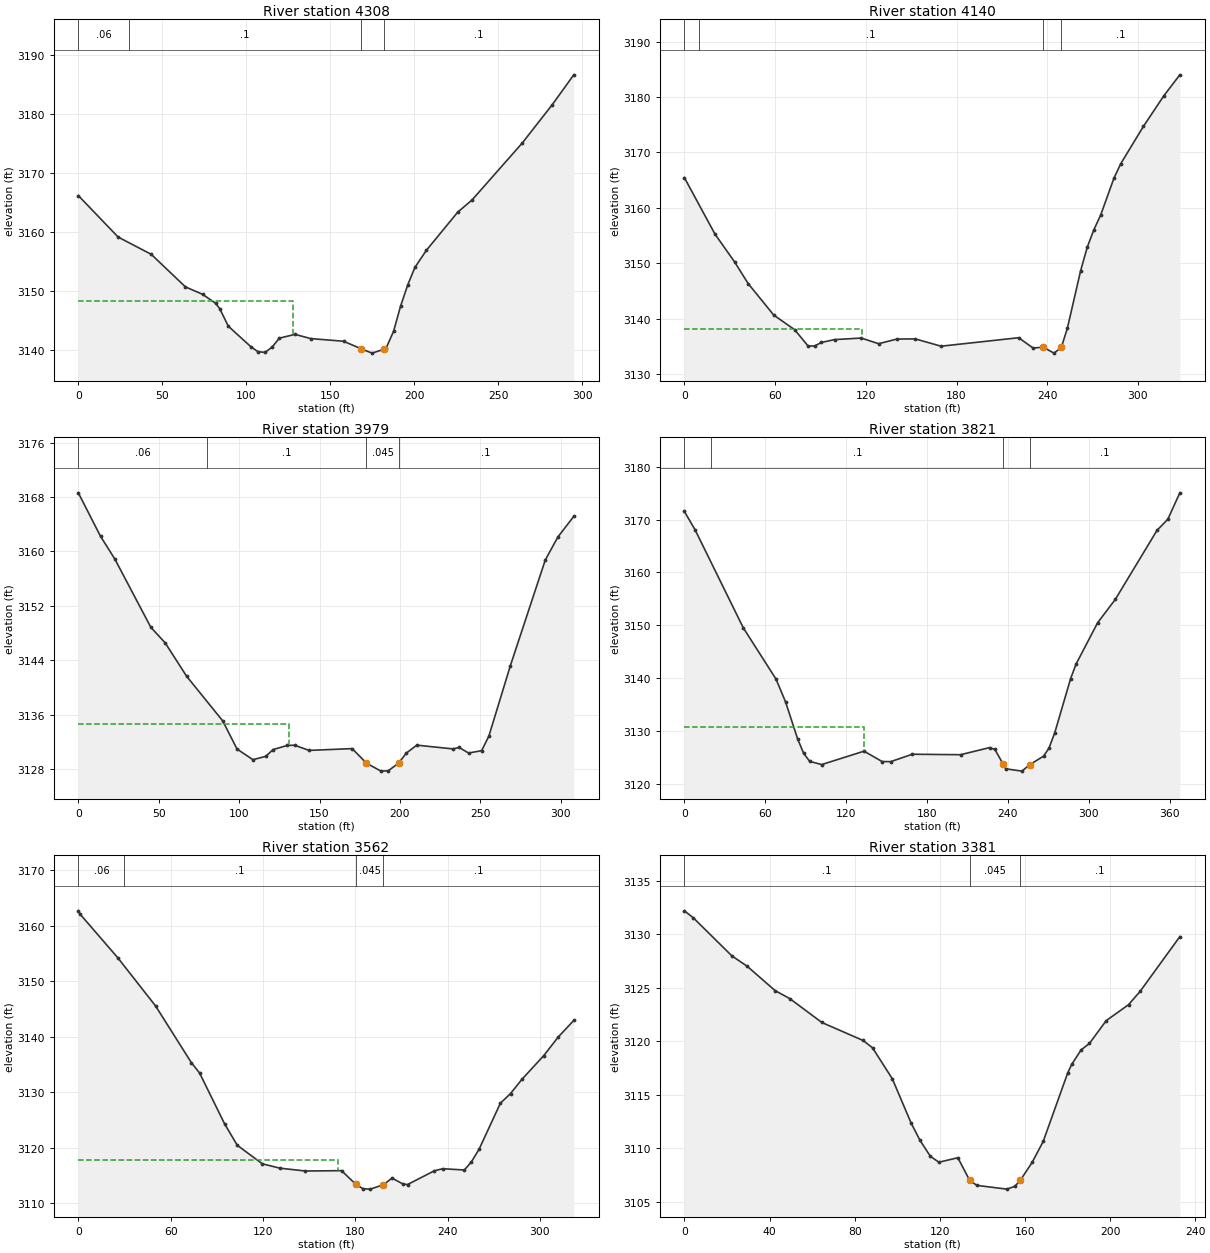
Type RM Length L Ch R = 1 ,4308    ,168,168,168
XS GIS Cut Line= 3
2340486.14619727572834.4908117852340558.91452961572892.099197025
2340749.18071339572960.531732977
#Sta/Elev= 30
       0  3166.2    23.7 3159.15    43.4 3156.22    63.8 3150.68      74 3149.42
    81.7 3147.91    84.2 3146.99    89.3 3144.01   102.7 3140.53   106.9 3139.68
   111.2 3139.55   115.4 3140.46   119.7 3141.97     129 3142.62   138.4  3141.9
   157.9 3141.45  168.433140.169   174.9 3139.43   182.2 3140.11   183.4 3140.37
   187.7 3143.13   191.9 3147.43   196.2 3151.06   200.4 3153.98   207.2 3156.88
   225.9 3163.38   234.4 3165.44   264.2 3175.08   282.2 3181.64     295 3186.71
#Mann= 4 ,-1,0
       0     .06       0      30      .1       0  168.43    .045       0
   182.2      .1       0
#XS Ineff= 2 , 0
          127.94 3148.32
Permanent Ineff=
       F       F
Bank Sta=168.43,182.2
XS Rating Curve= 0 ,0
Exp/Cntr=0.3,0.1

Type RM Length L Ch R = 1 ,4140    ,159.8,160.9,158.2
XS GIS Cut Line= 2
2340393.80620298  572981.18016292340691.78440722573117.531001876
#Sta/Elev= 30
       0 3165.44    20.2 3155.27    33.4 3150.16    42.2 3146.32    59.1 3140.64
      73 3137.98    81.8 3135.06    86.2 3135.06    90.6  3135.7    99.4 3136.21
     117 3136.49   128.5 3135.47   140.6 3136.31   152.7 3136.34   169.8 3135.02
   221.1 3136.55   230.7 3134.68   237.2 3134.85   244.5 3133.77   249.3 3134.79
   253.3 3138.23   262.1 3148.65   266.5 3152.91   270.9 3156.07   275.3 3158.65
   284.1 3165.32   288.6 3167.94   303.6 3174.68   317.2 3180.24   327.7 3183.99
#Mann= 4 ,-1,0
       0     .06       0      10      .1       0   237.2    .045       0
   249.3      .1       0
#XS Ineff= 2 , 0
          117.79  3138.2
Permanent Ineff=
       F       F
Bank Sta=237.2,249.3
XS Rating Curve= 0 ,0
Exp/Cntr(USF)=0,0
Exp/Cntr=0.3,0.1

Type RM Length L Ch R = 1 ,3979    ,163.3,157.9,151.9
XS GIS Cut Line= 2
2340331.86091321573095.8145497152340607.41065046573233.589418341
#Sta/Elev= 30
       0 3168.62    13.8 3162.23    22.7 3158.89    45.1 3148.84      54 3146.56
    67.4 3141.63    89.8 3135.08    98.7 3130.94   108.6 3129.37   116.6 3129.87
   121.1 3130.86     130 3131.47   134.5  3131.5   143.5 3130.74   170.3    3131
   179.2 3128.86   188.2 3127.69   192.7 3127.74  199.133128.846     204 3130.35
   210.5 3131.51   232.9 3130.96   236.8 3131.17   242.7 3130.35   250.8  3130.7
   255.3 3132.84   268.7 3143.22   290.4 3158.75   298.2 3162.12   308.1 3165.16
#Mann= 4 ,-1,0
       0     .06       0      80      .1       0   179.2    .045       0
  199.13      .1       0
#XS Ineff= 2 , 0
          130.93 3134.57
Permanent Ineff=
       F       F
Bank Sta=179.2,199.13
XS Rating Curve= 0 ,0
Exp/Cntr(USF)=0,0
Exp/Cntr=0.3,0.1

Type RM Length L Ch R = 1 ,3821    ,248,259.8,263.3
XS GIS Cut Line= 3
 2340257.0993566573234.6574405782340452.54742604 573332.91548642
2340601.00251704573343.595708794
#Sta/Elev= 30
       0 3171.52     7.9 3168.08    43.7 3149.55      68 3139.86    75.1 3135.54
      84 3128.59    88.5 3125.84      93 3124.32   101.9 3123.72   133.3 3126.25
   146.7 3124.29   153.1 3124.27   169.1 3125.67   204.9 3125.58   226.4 3126.92
   230.4 3126.57  236.613123.765   238.4 3122.92   250.5 3122.48   256.1 3123.68
   266.5 3125.31   270.5 3126.81   274.8 3129.72   286.6 3139.97   290.6 3142.69
   306.6  3150.5   319.7  3154.9   350.7 3167.96   358.7 3170.05   367.6 3175.04
#Mann= 4 ,-1,0
       0     .07       0      20      .1       0  236.61    .045       0
   256.1      .1       0
#XS Ineff= 2 , 0
          132.96 3130.85
Permanent Ineff=
       F       F
Bank Sta=236.61,256.1
XS Rating Curve= 0 ,0
Exp/Cntr(USF)=0,0
Exp/Cntr=0.3,0.1

Type RM Length L Ch R = 1 ,3562    ,177.3,180.4,178.6
XS GIS Cut Line= 3
2340179.00259208573475.6424472812340297.16947596573499.730804028
2340468.79262583573605.098004233
#Sta/Elev= 30
       0 3162.72     1.2 3162.11    25.7 3154.24    50.2 3145.57    73.5 3135.33
    78.8 3133.48    95.1 3124.29   103.3 3120.44   119.6  3117.1     131 3116.31
   147.6  3115.8   171.1 3115.86   180.4 3113.38   185.1  3112.6   189.8 3112.53
   198.3 3113.33   203.9 3114.52   211.1 3113.44     214 3113.36   231.4 3115.84
   236.8 3116.21   250.9 3115.98   255.5 3117.46   260.5 3119.75   274.3 3128.02
   280.9 3129.77   288.4 3132.36   302.5 3136.61   311.9 3139.96     322 3142.95
#Mann= 4 ,-1,0
       0     .06       0      30      .1       0   180.4    .045       0
   198.3      .1       0
#XS Ineff= 2 , 0
          168.54 3117.87
Permanent Ineff=
       F       F
Bank Sta=180.4,198.3
XS Rating Curve= 0 ,0
Exp/Cntr(USF)=0,0
Exp/Cntr=0.3,0.1

Type RM Length L Ch R = 1 ,3381    ,162.6,158,152.6
XS GIS Cut Line= 3
2340221.49861535573590.3088456352340252.47126023573659.018276241
2340393.80620298573728.439721673
#Sta/Elev= 30
       0 3132.17     4.2 3131.52    22.3 3127.97    29.5    3127    42.6 3124.73
    49.6 3123.97    64.6 3121.75      84 3120.07    88.4 3119.39    97.7  3116.5
   106.6 3112.34   110.7 3110.76   115.6 3109.26   119.6 3108.71   128.5 3109.13
  134.023107.036   137.4 3106.55   151.5  3106.2   155.3 3106.46  157.873107.033
   163.4 3108.69   168.6 3110.65   180.1 3117.03     182 3117.84   186.4 3119.19
   190.3 3119.79   198.2 3121.92   208.7 3123.41   214.2 3124.67   232.8 3129.76
#Mann= 3 ,-1,0
       0      .1       0  134.02    .045       0  157.87      .1       0
Bank Sta=134.02,157.87
XS Rating Curve= 0 ,0
Exp/Cntr(USF)=0,0
Exp/Cntr=0.3,0.1

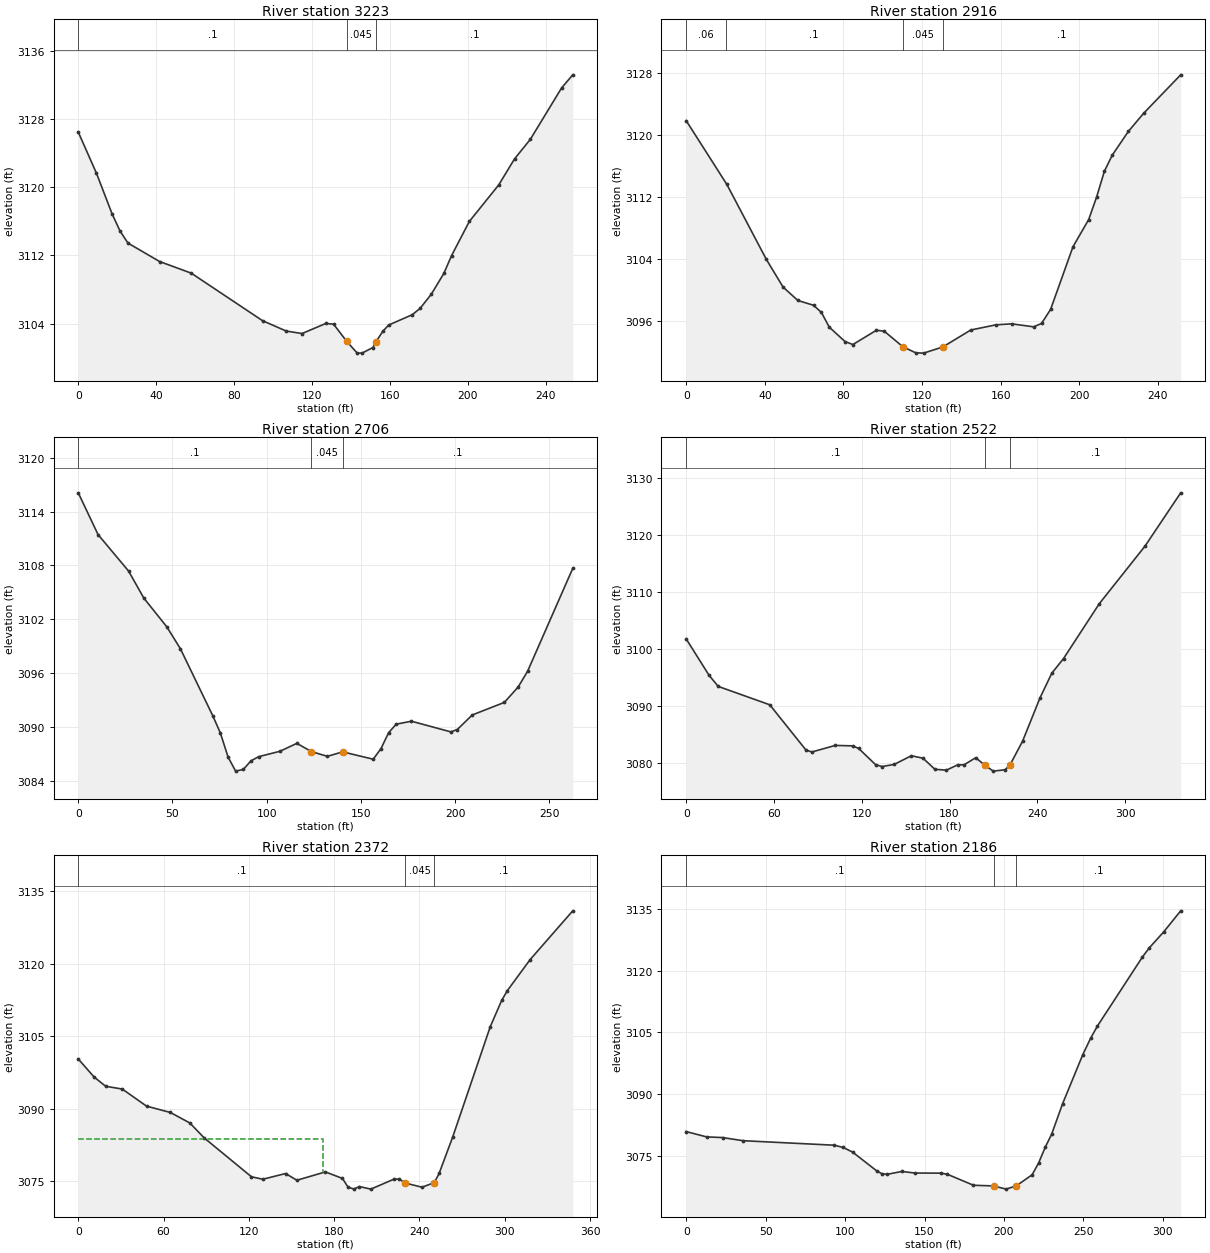
Type RM Length L Ch R = 1 ,3223    ,308.3,307.2,303
XS GIS Cut Line= 3
2340135.06792688573813.8419442862340261.25277641573836.389080409
2340385.85537077573853.398323449
#Sta/Elev= 30
       0 3126.48     9.3 3121.67    17.4 3116.86    21.4 3114.89    25.5 3113.45
    41.8 3111.28      58 3109.92    94.6 3104.34   106.8 3103.12   114.9 3102.83
   127.1 3104.01   131.1 3103.93  137.84 3101.91   143.2 3100.54   145.7 3100.53
   151.3 3101.19   152.8 3101.82   156.3 3103.08   159.4 3103.83   171.5 3105.04
   175.5 3105.78   181.2 3107.42   187.7 3109.88   191.7 3111.99   200.8 3115.99
   215.9 3120.28     224 3123.33   232.1 3125.62   248.2 3131.67   253.9  3133.2
#Mann= 3 ,-1,0
       0      .1       0  137.84    .045       0   152.8      .1       0
Bank Sta=137.84,152.8
XS Rating Curve= 0 ,0
Exp/Cntr(USF)=0,0
Exp/Cntr=0.3,0.1

Type RM Length L Ch R = 1 ,2916    ,207.3,210.3,213
XS GIS Cut Line= 3
2340091.50285445574118.6738564342340158.21392523574122.827849003
2340342.93094167574121.157811351
#Sta/Elev= 30
       0 3121.86    20.7 3113.61    40.8 3103.91    49.3 3100.34    56.8 3098.61
    64.8 3097.99    68.8 3097.06    72.8 3095.16    80.8  3093.3    84.8 3092.91
    96.8 3094.76   100.8 3094.63   110.33092.613   116.8 3091.84   120.8  3091.8
  130.553092.597   144.8 3094.79   157.6 3095.46   165.6 3095.59   176.8  3095.2
   180.8 3095.64   185.4 3097.45   196.8 3105.56   204.8 3109.08   208.8 3111.97
   212.8 3115.34   216.8 3117.41     225 3120.48   232.8 3122.83   251.6 3127.79
#Mann= 4 ,-1,0
       0     .06       0      20      .1       0   110.3    .045       0
  130.55      .1       0
Bank Sta=110.3,130.55
XS Rating Curve= 0 ,0
Exp/Cntr(USF)=0,0
Exp/Cntr=0.3,0.1

Type RM Length L Ch R = 1 ,2706    ,184.4,183.6,179.9
XS GIS Cut Line= 3
2340021.81947838574300.141232814 2340195.1838562574329.442254417
2340280.94227024574341.487107119
#Sta/Elev= 30
       0 3116.11    10.5 3111.45    26.7 3107.38    34.8 3104.36      47 3101.15
    54.2 3098.71    71.4 3091.22    75.4 3089.31    79.5 3086.62    83.5 3085.05
    87.6 3085.24    91.6 3086.19    95.7 3086.66   107.1 3087.27     116 3088.15
   123.7 3087.23   132.2  3086.7   140.3  3087.2   156.5 3086.38   160.6 3087.55
   164.7 3089.34   168.7 3090.29   176.8 3090.62   197.7 3089.43   201.1 3089.69
   209.1 3091.32   226.1 3092.72   233.4 3094.43   238.4 3096.18   262.4 3107.68
#Mann= 3 ,-1,0
       0      .1       0   123.7    .045       0   140.3      .1       0
Bank Sta=123.7,140.3
XS Rating Curve= 0 ,0
Exp/Cntr(USF)=0,0
Exp/Cntr=0.3,0.1

Type RM Length L Ch R = 1 ,2522    ,150.1,149.9,148.9
XS GIS Cut Line= 4
2339946.61352294574460.8085012672340001.30876326 574492.06292431
2340213.74116988 574494.504676112340272.34321308574516.480442312
#Sta/Elev= 30
       0 3101.77    15.6  3095.4    21.9 3093.44    57.1 3090.22    81.9 3082.27
    85.9 3081.94   101.9 3083.09   113.9 3083.01   117.9 3082.55   129.5  3079.7
   133.9 3079.39   142.1 3079.75   153.9 3081.28   161.9 3080.84     170  3078.9
   177.9 3078.75   185.6 3079.69   189.9 3079.69   197.9 3080.93   204.23079.598
   209.9 3078.58   217.9 3078.82   221.2 3079.61   229.9 3083.82   241.9 3091.47
   249.9 3095.76   257.9 3098.32   282.3 3107.93   313.6 3118.05     338  3127.4
#Mann= 3 ,-1,0
       0      .1       0   204.2    .045       0   221.2      .1       0
Bank Sta=204.2,221.2
XS Rating Curve= 0 ,0
Exp/Cntr(USF)=0,0
Exp/Cntr=0.3,0.1

Type RM Length L Ch R = 1 ,2372    ,181.9,186.2,189.1
XS GIS Cut Line= 3
2339907.05714377574587.291244518 2339978.8446467574639.056382682
2340238.15868788574638.568032322
#Sta/Elev= 30
       0 3100.29    11.2 3096.54    19.3 3094.64      31 3094.06      48 3090.53
    64.8 3089.21    78.5 3087.03    88.5 3083.96   121.8 3075.89   129.8 3075.38
   145.8 3076.56   153.8 3075.17   173.8  3076.9   185.8 3075.55   189.8 3073.73
   193.8 3073.36   197.8 3073.86   205.8 3073.33   221.8 3075.37   225.8 3075.41
   229.8 3074.61   241.8 3073.72  250.43 3074.69   253.8 3076.57   263.4 3084.16
   289.8    3107   297.8 3112.42   301.8 3114.46   317.8 3120.88   347.8 3130.99
#Mann= 3 ,-1,0
       0      .1       0   229.8    .045       0  250.43      .1       0
#XS Ineff= 2 , 0
          172.14 3083.63
Permanent Ineff=
       F       F
Bank Sta=229.8,250.43
XS Rating Curve= 0 ,0
Exp/Cntr(USF)=0,0
Exp/Cntr=0.3,0.1

Type RM Length L Ch R = 1 ,2186    ,210.1,212.3,209.2
XS GIS Cut Line= 3
2339936.84651574574707.9137834482339969.56598986574789.468293574
2340187.37025044574838.791679938
#Sta/Elev= 30
       0 3080.83    12.8 3079.54    22.9 3079.37    35.8 3078.61    93.2 3077.51
    98.8 3076.96   104.7 3075.84   119.9 3071.26   123.4 3070.52   126.6 3070.44
   135.7 3071.12   143.9 3070.74   160.3 3070.71   164.4 3070.43   180.8 3067.76
   193.5  3067.6   201.3 3066.82  207.743067.614   217.7 3070.31   221.8 3073.19
   225.9 3076.97     230 3080.21   236.9 3087.63   249.6 3099.57   254.6 3103.61
   258.7 3106.46   287.1 3123.32   291.5 3125.59   300.5 3129.44   311.2 3134.57
#Mann= 3 ,-1,0
       0      .1       0   193.5    .045       0  207.74      .1       0
Bank Sta=193.5,207.74
XS Rating Curve= 0 ,0
Exp/Cntr(USF)=0,0
Exp/Cntr=0.3,0.1

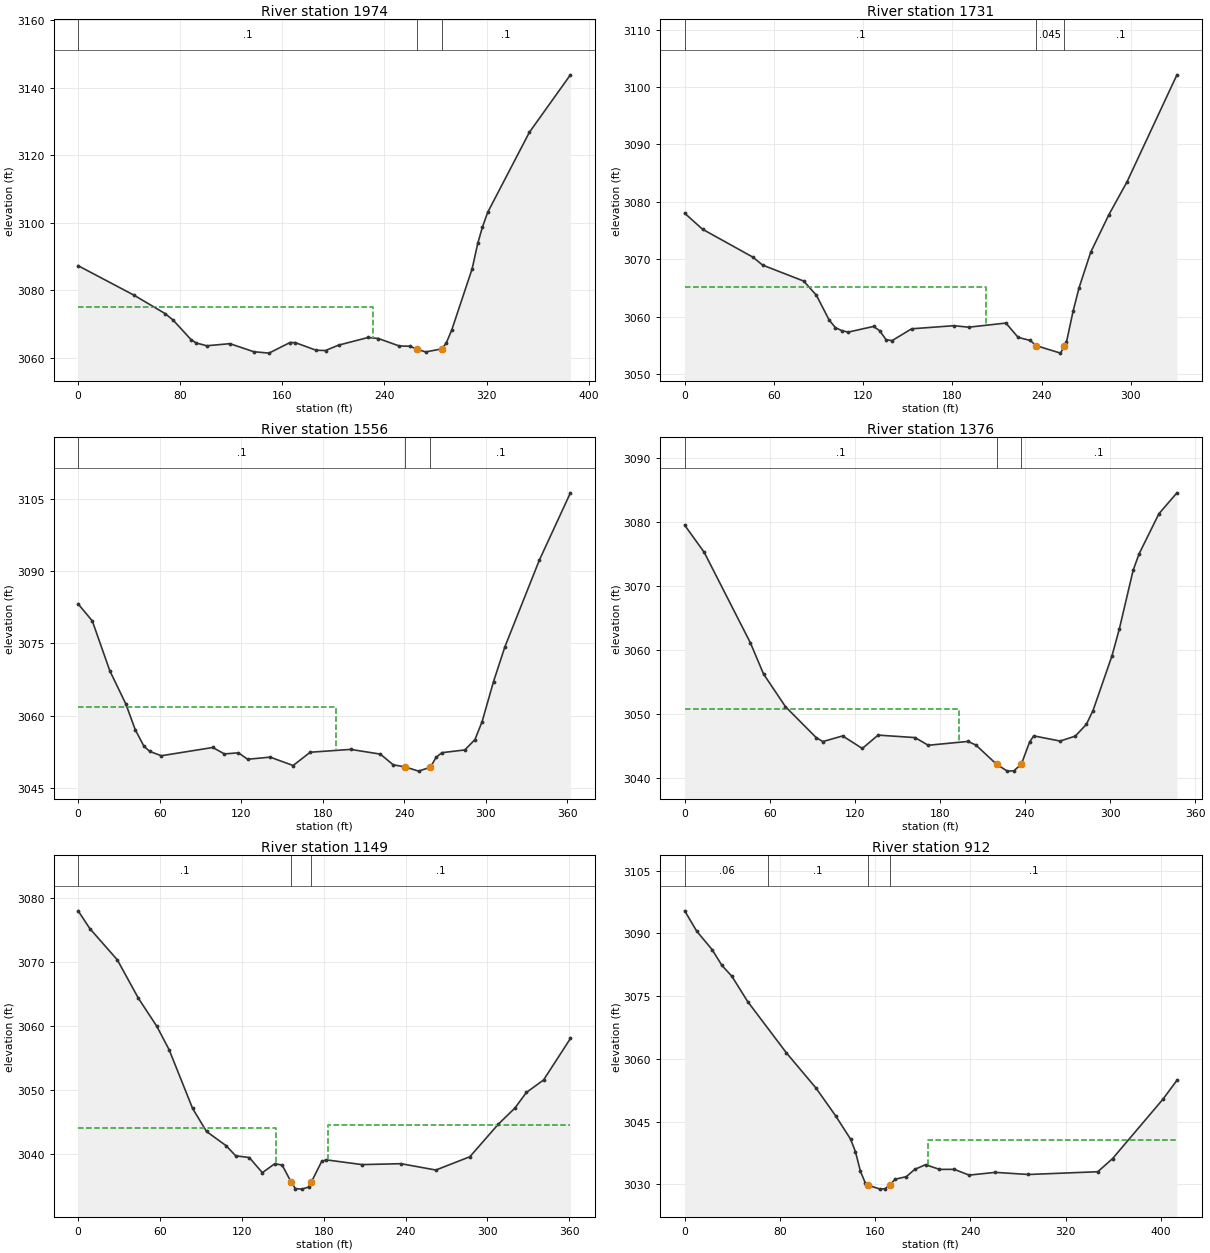
Type RM Length L Ch R = 1 ,1974    ,249,242.8,238.8
XS GIS Cut Line= 2
2339793.27150988574952.5773138282340171.74303892575026.806568554
#Sta/Elev= 30
       0 3087.31    43.7  3078.6    68.2 3073.13    74.6 3071.15    88.6 3065.37
    92.6 3064.43   100.8 3063.62   118.9 3064.24   137.5 3061.87   149.5 3061.44
     166 3064.58   170.1 3064.55   186.4  3062.3   193.8 3062.21     204  3063.8
   227.2 3066.07   235.3 3065.76   251.6 3063.55   259.8 3063.48   265.4 3062.66
   272.2 3061.79   284.73062.677   288.3 3064.33   292.7 3068.28   308.7  3086.4
   313.1 3093.94   316.8 3098.79   320.9 3103.11   353.5 3126.76   385.7 3143.79
#Mann= 3 ,-1,0
       0      .1       0   265.4    .045       0   284.7      .1       0
#XS Ineff= 2 , 0
          230.76 3074.95
Permanent Ineff=
       F       F
Bank Sta=265.4,284.7
XS Rating Curve= 0 ,0
Exp/Cntr(USF)=0,0
Exp/Cntr=0.3,0.1

Type RM Length L Ch R = 1 ,1731    ,165.8,175.3,180.5
XS GIS Cut Line= 3
  2339777.155948575132.778596682 2339969.0776395575204.077749248
2340093.11863095575180.636931966
#Sta/Elev= 30
       0 3078.02      12 3075.23    45.9 3070.36    52.4 3068.98      80  3066.2
    88.6 3063.72    97.1 3059.43   101.4 3058.07   105.6 3057.57   109.9  3057.3
     127 3058.29   131.2 3057.53   135.5 3055.95   139.6 3055.84   152.6 3057.88
     181 3058.42     191 3058.16     216 3058.88   224.2 3056.39   232.3 3055.85
   236.4 3054.94   252.7 3053.64   255.2 3054.81   256.7 3055.54   261.2 3060.98
   265.2 3065.04     273 3071.21   285.2 3077.74   297.4 3083.47     331 3102.13
#Mann= 3 ,-1,0
       0      .1       0   236.4    .045       0   255.2      .1       0
#XS Ineff= 2 , 0
          202.31 3065.23
Permanent Ineff=
       F       F
Bank Sta=236.4,255.2
XS Rating Curve= 0 ,0
Exp/Cntr(USF)=0,0
Exp/Cntr=0.3,0.1

Type RM Length L Ch R = 1 ,1556    ,175.6,180.1,182.1
XS GIS Cut Line= 2
 2339738.0879192575286.1206097352340081.88657267575400.394593984
#Sta/Elev= 30
       0 3083.22    10.4 3079.69    23.3 3069.32    35.1  3062.4      42 3057.08
    48.4 3053.62    52.8 3052.53    61.2 3051.64    99.1 3053.36   107.6 3052.02
     118 3052.25   124.7 3050.91   141.3 3051.35   158.2 3049.61   170.8 3052.37
   200.5 3052.96   222.4 3051.98   231.9 3049.75   240.43049.337   250.6 3048.44
   259.3 3049.27   263.5 3051.34   267.8 3052.28   284.6 3052.85     292 3054.99
   297.3 3058.73   305.7 3067.07   314.1 3074.32   339.4 3092.31   362.3 3106.33
#Mann= 3 ,-1,0
       0      .1       0   240.4    .045       0   259.3      .1       0
#XS Ineff= 2 , 0
          189.75 3061.72
Permanent Ineff=
       F       F
Bank Sta=240.4,259.3
XS Rating Curve= 0 ,0
Exp/Cntr(USF)=0,0
Exp/Cntr=0.3,0.1

Type RM Length L Ch R = 1 ,1376    ,219.7,226.4,231.7
XS GIS Cut Line= 2
2339708.29854724575407.7198493852340007.16896758 575584.50267972
#Sta/Elev= 30
       0 3079.54    13.8 3075.28    46.3 3061.14    55.6 3056.25    71.1 3051.12
    92.8 3046.27    97.5 3045.66   111.4 3046.54   125.3 3044.58   136.4 3046.67
   162.5 3046.28   171.8 3045.08   199.7 3045.68   205.4 3045.12     220  3042.1
   227.6 3041.03   232.2 3041.08   237.5 3042.13   243.3  3045.6   246.2 3046.55
   264.8 3045.74   275.5 3046.51   283.3 3048.35     288 3050.51   301.4 3059.09
   306.6 3063.32   316.3 3072.47   320.5 3075.05   334.5 3081.33   347.2  3084.6
#Mann= 3 ,-1,0
       0      .1       0     220    .045       0   237.5      .1       0
#XS Ineff= 2 , 0
          193.63 3050.74
Permanent Ineff=
       F       F
Bank Sta=220,237.5
XS Rating Curve= 0 ,0
Exp/Cntr(USF)=0,0
Exp/Cntr=0.3,0.1

Type RM Length L Ch R = 1 ,1149    ,246.6,237.2,228.5
XS GIS Cut Line= 3
2339643.34794935575525.412286155  2339777.155948575722.705831611
2339895.33673513575754.448605013
#Sta/Elev= 30
       0 3078.02     8.6 3075.23    28.7 3070.35    44.2 3064.32    57.7 3059.93
    66.7 3056.27    83.9 3047.08    94.1 3043.48   108.4 3041.27   115.5 3039.67
   125.4 3039.41     135 3037.04     144 3038.42   149.5 3038.24   155.9 3035.65
   159.2 3034.55     164 3034.46   168.9 3034.79     1713035.606   178.5  3038.8
   181.9 3039.04   208.1  3038.3   236.6 3038.44   262.2 3037.45   287.1 3039.53
   307.8 3044.59   320.2 3047.17   328.5 3049.59   341.1 3051.54   360.8 3058.04
#Mann= 3 ,-1,0
       0      .1       0   155.9    .045       0     171      .1       0
#XS Ineff= 2 ,-1
       0   144.7    3044  183.44360.7585 3044.51
Permanent Ineff=
       F       F
Bank Sta=155.9,171
XS Rating Curve= 0 ,0
Exp/Cntr(USF)=0,0
Exp/Cntr=0.3,0.1

Type RM Length L Ch R = 1 ,912     ,317.6,325.9,327.1
XS GIS Cut Line= 2
2339454.02800368575798.1516978132339852.24084108575909.055833838
#Sta/Elev= 30
       0 3095.39    10.2 3090.49      23 3086.13    31.3 3082.33    39.6 3079.76
    52.9  3073.7    85.4 3061.44   110.2 3053.04   126.8 3046.36   139.3  3040.8
   143.4 3037.81   147.6 3033.11   151.7  3030.3   153.6 3029.81   164.2 3028.84
   168.3 3028.95   172.5 3029.88   176.6  3031.2   186.1 3031.82   193.2 3033.56
   202.3 3034.69     214 3033.56   226.4 3033.57   238.9 3032.19   260.8 3032.85
   288.7 3032.34   346.9    3033   359.3 3036.13   401.6 3050.33   413.4 3054.86
#Mann= 4 ,-1,0
       0     .06       0      70      .1       0   153.6    .045       0
   172.5      .1       0
#XS Ineff= 1 ,-1
  204.23413.3681  3040.6
Permanent Ineff=
       F
Bank Sta=153.6,172.5
XS Rating Curve= 0 ,0
Exp/Cntr(USF)=0,0
Exp/Cntr=0.3,0.1

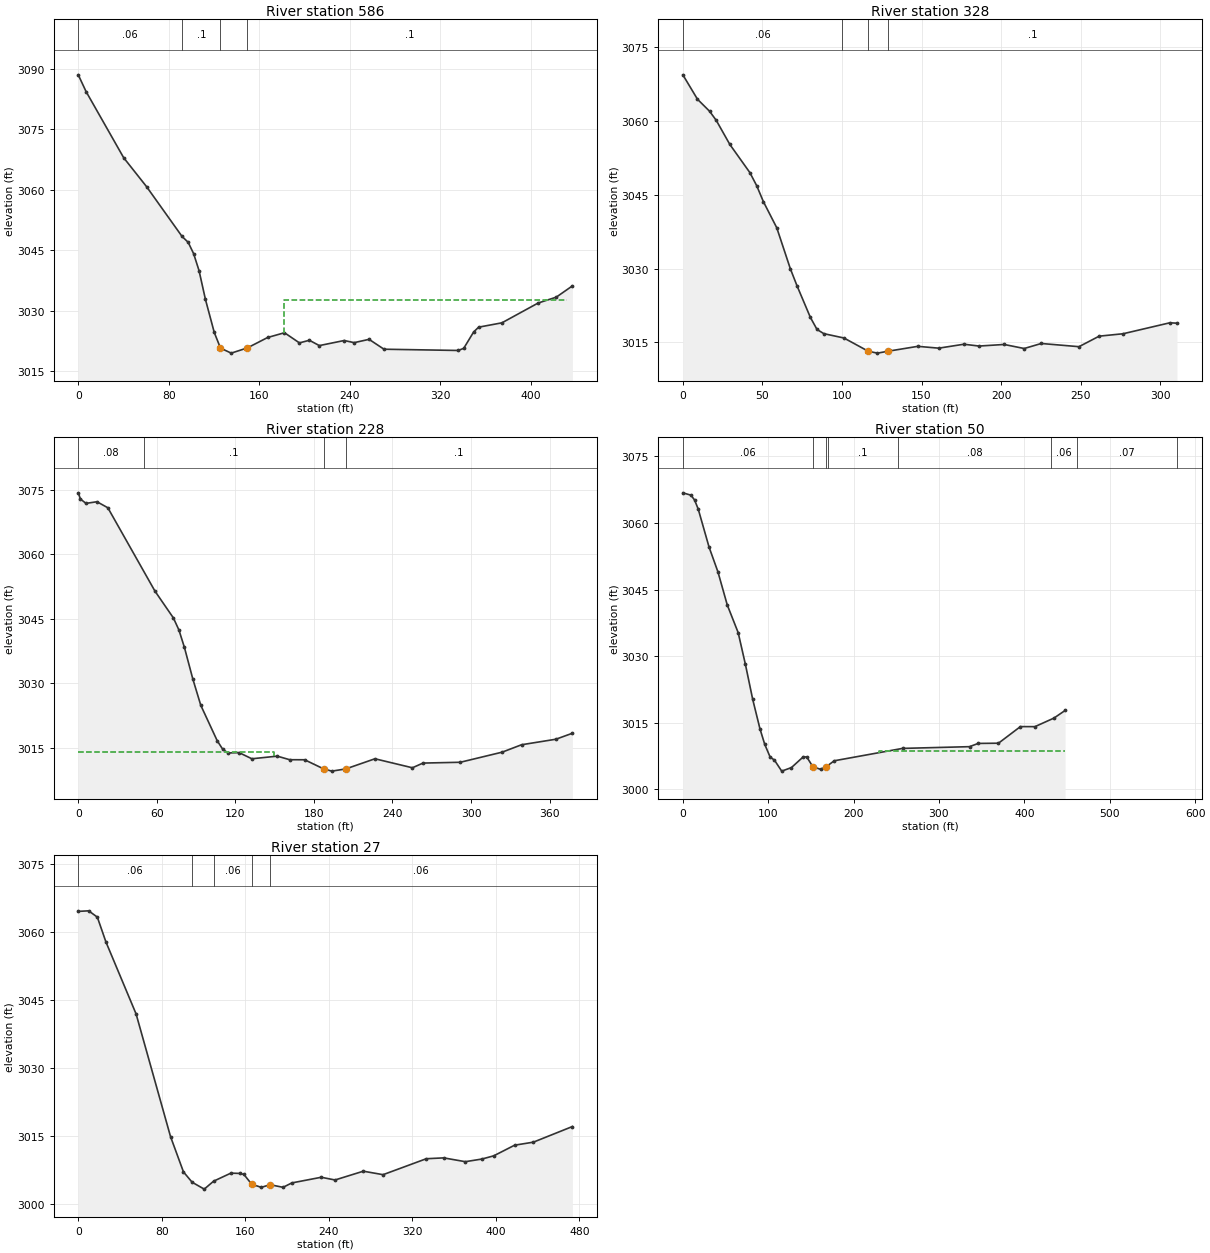
Type RM Length L Ch R = 1 ,586     ,262.1,258.4,251
XS GIS Cut Line= 4
 2339374.3854362576047.4999231042339522.50572525576142.773274857
2339690.36178697576220.1035364752339766.45353943576220.095915106
#Sta/Elev= 30
       0 3088.51     6.9 3084.37    40.2 3067.93    60.4 3060.77    91.8 3048.41
    97.2 3046.96     102 3044.16   106.8 3039.96   112.5 3032.77   120.3 3024.58
   125.8  3020.7   135.3 3019.46   149.6 3020.76   167.5 3023.34   182.4 3024.52
   195.6    3022   204.4 3022.65   213.2 3021.33   235.2 3022.59     244 3022.06
   257.2 3022.88   270.4 3020.43     336 3020.12   340.9 3020.65   349.7 3024.72
   354.1  3025.9   374.7 3026.98   406.7 3031.89   422.7 3033.34     437 3036.14
#Mann= 4 ,-1,0
       0     .06       0    91.8      .1       0   125.8    .045       0
   149.6      .1       0
#XS Ineff= 1 ,-1
   182.2 432.1513032.584
Permanent Ineff=
       F
Bank Sta=125.8,149.6
XS Rating Curve= 0 ,0
Exp/Cntr(USF)=0,0
Exp/Cntr=0.3,0.1

Type RM Length L Ch R = 1 ,328     ,107.5,100,92.2
XS GIS Cut Line= 3
2339332.23067618576329.4570825422339582.35040682576413.511265919
2339628.67776387576408.116223901
#Sta/Elev= 30
       0 3069.39     9.2 3064.42    16.8 3061.98      21 3060.12    29.5 3055.24
    42.1 3049.51    46.4 3046.84    50.6  3043.6      59 3038.29    67.5 3029.99
    71.7 3026.51    80.1 3020.08    84.3  3017.6    88.6 3016.75   101.2 3015.87
   116.6 3013.16   122.3 3012.79   129.2 3013.19   147.6 3014.17   160.8  3013.8
   176.6  3014.6   186.1 3014.23   201.9 3014.55   214.5 3013.73   225.2 3014.75
   248.9  3014.1   261.6 3016.24   276.6 3016.73     306 3018.96   310.5 3018.88
#Mann= 4 ,-1,0
       0     .06       0     100      .1       0   116.6    .045       0
   129.2      .1       0
Bank Sta=116.6,129.2
XS Rating Curve= 0 ,0
Exp/Cntr(USF)=0,0
Exp/Cntr=0.3,0.1

Type RM Length L Ch R = 1 ,228     ,170.6,178,182
XS GIS Cut Line= 5
 2339278.5087885576417.9239554782339450.71161676576469.315808237
2339479.39792142576461.5466007242339560.07815329576478.280278444
2339618.78598651576416.054889795
#Sta/Elev= 30
       0 3074.24     1.7  3072.8     5.9 3071.79    14.3 3072.17    22.6 3070.77
    58.6  3051.4    72.7 3045.16    76.9 3042.37    81.1 3038.32    87.5    3031
    93.6 3024.87   106.1 3016.67   110.3 3014.69   114.4 3013.81   122.9 3013.88
   132.6 3012.46     152 3013.07   161.5 3012.24   172.9 3012.23   187.5  3010.1
   193.7 3009.59   204.3  3010.1   226.6 3012.46   255.2 3010.37   263.3 3011.46
   291.8 3011.65   323.8    3014   338.6 3015.72   364.8    3017   377.4 3018.39
#Mann= 4 ,-1,0
       0     .08       0      50      .1       0   187.5    .045       0
   204.3      .1       0
#XS Ineff= 2 , 0
          149.81 3013.93
Permanent Ineff=
       F       F
Bank Sta=187.5,204.3
XS Rating Curve= 0 ,0
Exp/Cntr(USF)=0,0
Exp/Cntr=0.3,0.1

Type RM Length L Ch R = 1 ,50      ,26.9,23,17.3
XS GIS Cut Line= 6
2339259.28112726576579.1603487872339389.79165014576626.515236985
2339431.70818718 576629.650888232339475.84257411576567.761519039
2339557.33507381576499.6402459352339617.13456506576439.840754679
#Sta/Elev= 30
       0 3066.81     9.5 3066.28    13.7  3065.2      18 3063.15    30.7 3054.58
    41.1    3049      52 3041.56    64.8 3035.31    73.3 3028.14    81.8  3020.3
    90.3 3013.66    95.9 3010.16   102.2  3007.3   107.3 3006.59   115.8 3004.12
   127.2 3004.92   141.2 3007.37   145.2 3007.29   152.33005.094   161.3 3004.53
  167.823005.099   177.3 3006.45   257.3 3009.24   335.8 3009.63   345.9 3010.36
   369.7 3010.41   395.4 3014.15   412.4 3014.14   434.7 3016.07   447.7 3017.78
#Mann= 8 ,-1,0
       0     .06       0   152.3    .045       0  167.82     .06       0
   169.6      .1       0   252.2     .08       0   431.1     .06       0
   461.1     .07       0   578.8      .1       0
#XS Ineff= 2 , 0
                             230         3008.55
Permanent Ineff=
       F       F
Bank Sta=152.3,167.82
XS Rating Curve= 0 ,0
Exp/Cntr=0.3,0.1

Type RM Length L Ch R = 1 ,27      ,,,
XS GIS Cut Line= 4
2339242.46474728576620.1406275042339389.01291021576657.412992644
2339443.22725951576641.3181076982339622.81229154576445.638190713
#Sta/Elev= 30
       0 3064.63      10 3064.75    18.3 3063.35    26.5 3057.89    55.4 3041.99
    88.4  3014.9   100.8  3007.1   109.1 3004.82   120.7  3003.3   129.7 3005.06
   146.2 3006.83   154.5 3006.77   158.7 3006.54   166.1  3004.4   175.4 3003.69
   183.7 3004.28   196.2  3003.7   204.6 3004.67   232.8 3005.92     246 3005.32
   273.1 3007.26     292 3006.49   333.4 3010.01   350.1  3010.2   370.8 3009.36
   386.6 3009.94     398 3010.65     418    3013     436 3013.67473.3631 3017.12
#Mann= 5 ,-1,0
       0     .06       0   109.1    .045       0   129.7     .06       0
   166.1    .045       0   183.7     .06       0
Bank Sta=166.1,183.7
XS Rating Curve= 0 ,0
Exp/Cntr(USF)=0,0
Exp/Cntr=0.3,0.1
LCMann Table=0

Chan Stop Cuts=-1
Use User Specified Reach Order=0
Composite Channel Slope=5